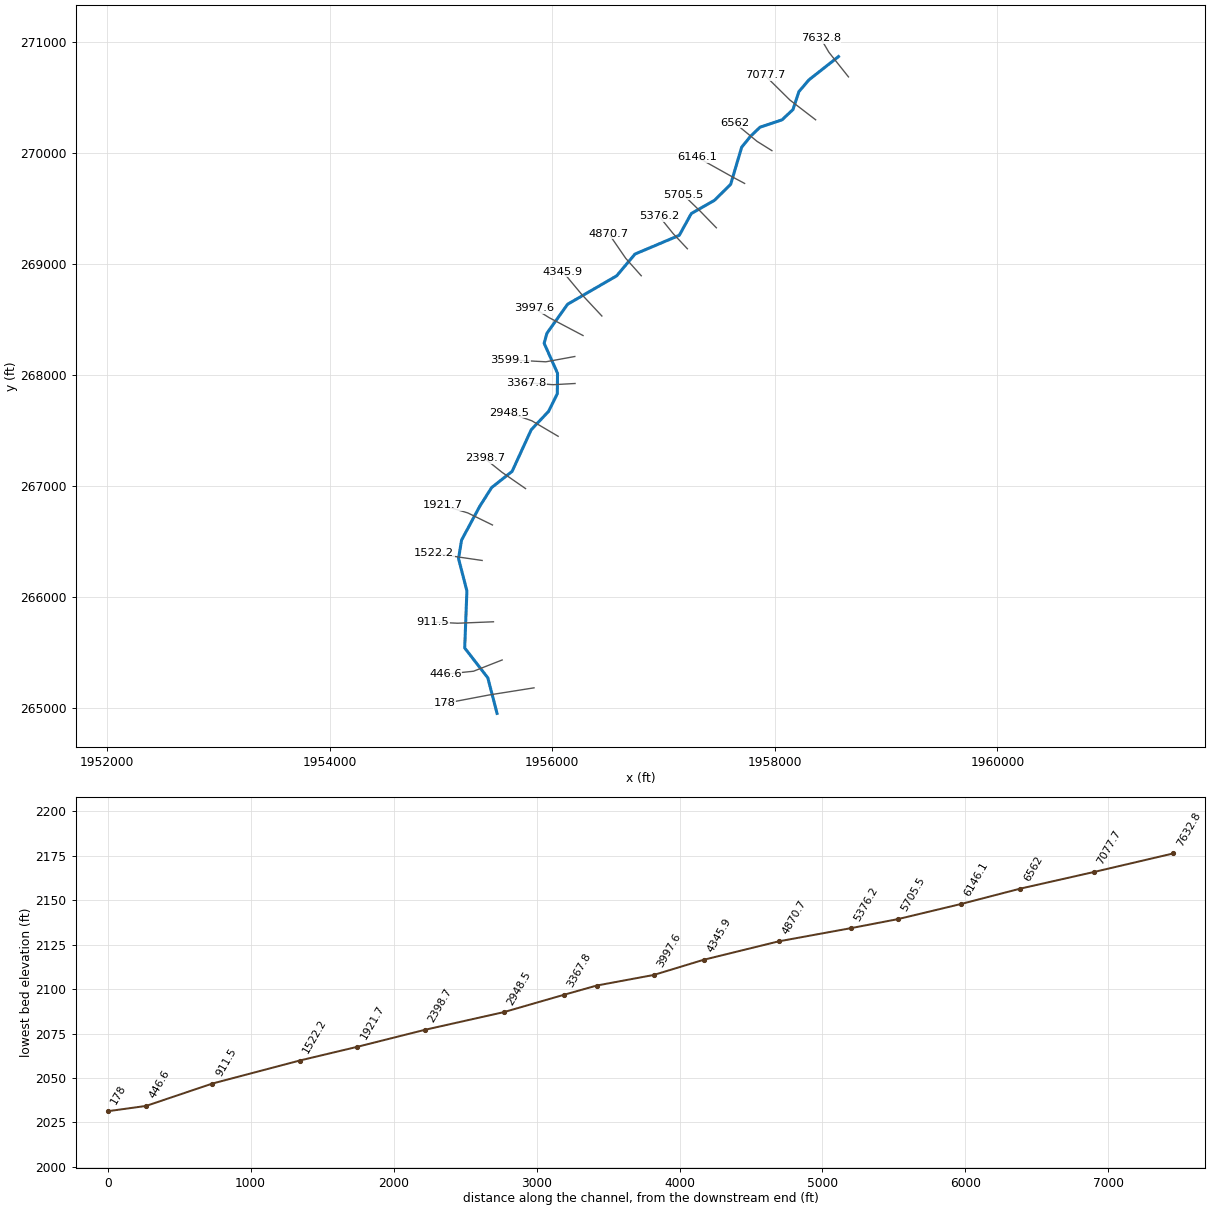
--- NOBRWOLFRN.prj (project) ---

Proj Title=NOBRWOLFRN
Current Plan=p01
Default Exp/Contr=0,0
English Units
Geom File=g01
Flow File=f01
Plan File=p01
BEGIN DESCRIPTION:
END DESCRIPTION:
DSS Export Rating Curves= 0
DSS Export Rating Curve Sorted= 0
DSS Export Volume Flow Curves= 0
DXF OffsetX= 0
DXF OffsetY= 0
DXF ScaleX= 0
DXF ScaleY= 0

--- NOBRWOLFRN.p01 (plan) ---

Plan Title=Floodplain
Program Version=4.00
Geom File=g01
Flow File=f01
K Sum by GR=0
Std Step Tol=0.01
Critical Tol=0.01
Num of Std Step Trials=20
Max Error Tol=0.3
Flow Tol Ratio=0.001
Split Flow NTrial=30
Split Flow Tol=0.02
Split Flow Ratio=0.02
Log Output Level=0
Friction Slope Method=1
Unsteady Friction Slope Method=2
Unsteady Bridges Friction Slope Method=1
Global Log Level=0
CheckData=False
Run HTab=0
Run UNet=0
Run PostProcess=0
UNET Theta=0
UNET Theta Warmup=0
UNET ZTol=0
UNET ZSATol=0
UNET MxIter=0
UNET MaxInSteps=0
UNET DtIC=0
UNET DtMin=0
UNET MaxCRTS=0
UNET WFStab=0
UNET SFStab=0
UNET WFX=0
UNET SFX=0
UNET DSS MLevel=0
UNET DZMax Abort=0
UNET Convert EG Bridges=0
UNET Use Existing IB Tables=0
UNET Froude Limit=0
UNET Froude Power=0
Write IC File=0
Echo Input=False
Echo Output=False
Write Detailed=0

--- NOBRWOLFRN.f01 (steady flow) ---

Flow Title=NFF Regression Equation
Program Version=4.00
Number of Profiles=1
Profile Names=P100yr
River Rch & RM=NOBRWOLFRN,Main      ,7632.8
529.4512
River Rch & RM=NOBRWOLFRN,Main      ,6146.1
548.1061
River Rch & RM=NOBRWOLFRN,Main      ,4345.9
596.9879
River Rch & RM=NOBRWOLFRN,Main      ,3367.8
632.8563
River Rch & RM=NOBRWOLFRN,Main      ,178
687.2362
Boundary for River Rch & Prof#=NOBRWOLFRN,Main      ,1
Up Type=0
Dn Type=3
Dn Slope=0.019851

--- NOBRWOLFRN.g01 (geometry) ---

Geom Title=USGS 10m DEM
Program Version=4.10

River Reach=NOBRWOLFRN      ,Main
Reach XY= 30
     1958572.637      270868.096     1958307.012      270658.461
     1958217.168      270552.992     1958163.783      270391.534
     1958066.127      270299.086      1957868.21       270232.68
     1957782.272      270150.648     1957702.845      270052.124
     1957603.887      269718.357     1957458.054      269573.825
     1957250.534      269455.447     1957142.081      269258.721
     1956744.512      269090.318     1956579.581      268894.138
     1956138.816      268638.501     1955952.845      268376.777
     1955928.052      268287.322     1956048.331      268017.402
     1956046.595      267833.374     1955967.846       267673.66
      1955812.22      267508.721     1955640.345      267133.721
     1955456.317      266987.888     1955350.545      266820.563
      1955186.48      266515.827     1955158.987      266348.428
     1955234.095      266057.332     1955214.466      265543.769
     1955422.031      265274.868     1955504.929      264954.902

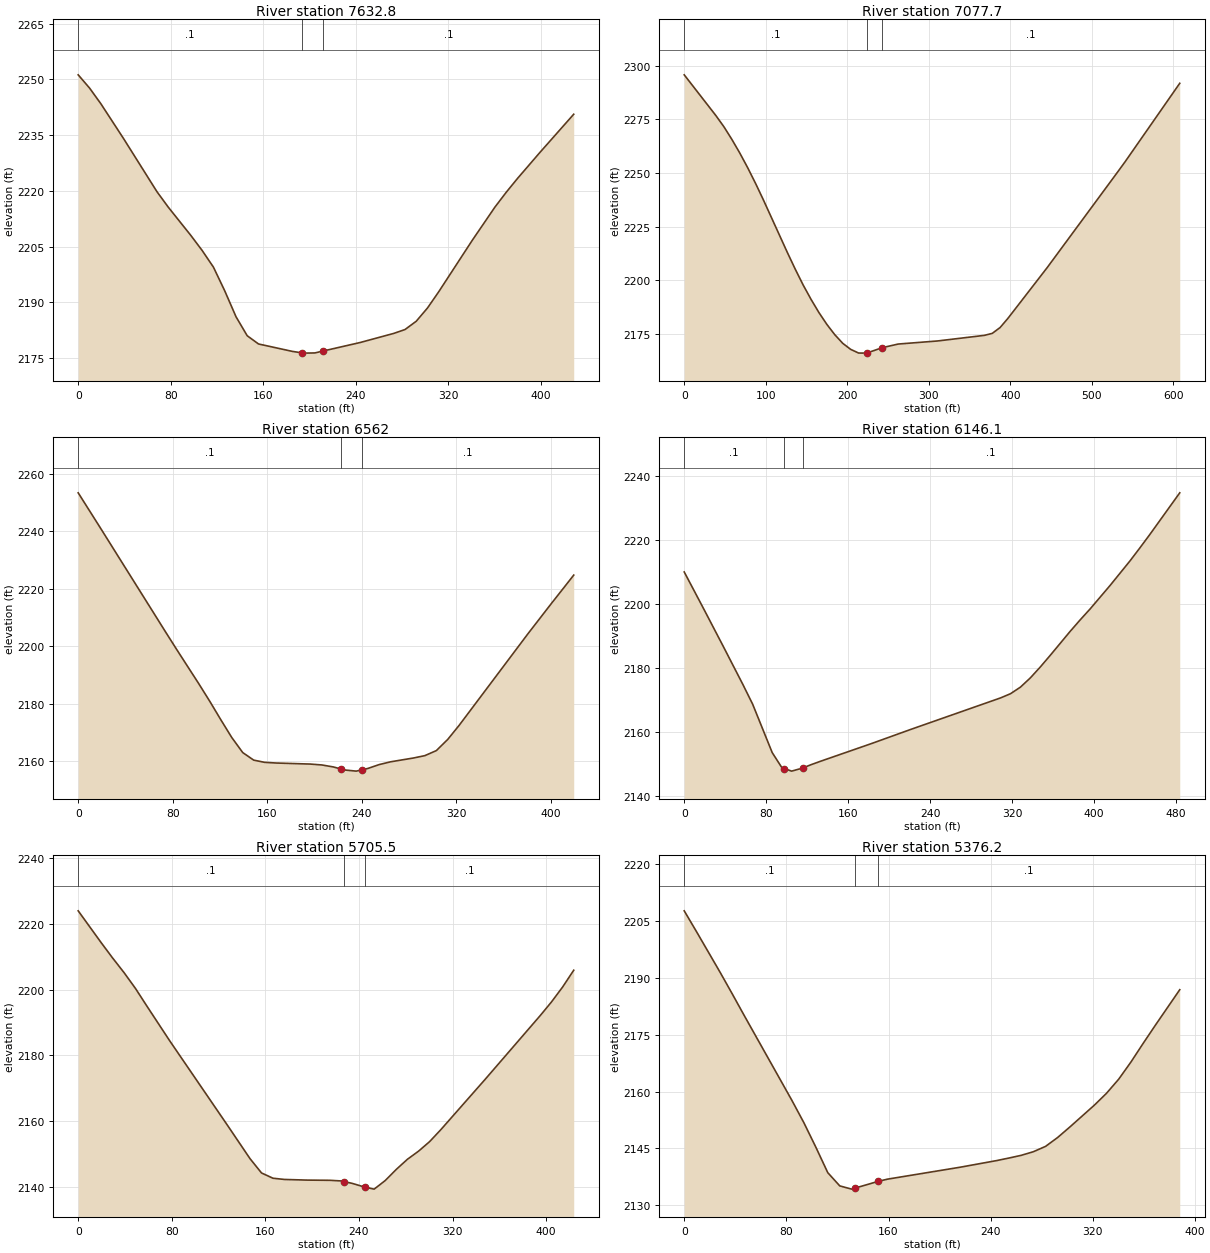
Type RM Length L Ch R = 1 ,7632.8  ,549.1,555.1,560.3
XS GIS Cut Line= 3
      1958662.51      270685.371     1958486.728      270906.725
     1958412.944      271032.593
#Sta/Elev= 30
       0 2251.21     9.8 2247.66    19.5 2243.48      39 2234.18    68.2 2219.74
      78 2215.58    97.5 2207.98   107.2 2203.97     117 2199.47   126.7 2193.14
   136.5 2186.14   146.2 2181.02     156 2178.81   185.2 2176.82   193.7 2176.41
   194.9 2176.35   204.7  2176.4   211.7 2176.91   243.7 2179.19   272.9 2181.65
   282.7  2182.7   292.4 2184.93   302.1 2188.48   311.8 2192.84     341 2206.77
   360.5 2215.65   370.2 2219.61   379.9 2223.31   399.4 2230.35   428.6 2240.61
#Mann= 3 , 0 , 0
       0      .1       0   193.7    .045       0   211.7      .1       0
Bank Sta=193.7,211.7
XS Rating Curve= 0 ,0
Exp/Cntr=0.3,0.1

Type RM Length L Ch R = 1 ,7077.7  ,515.8,515.7,515.4
XS GIS Cut Line= 3
     1958367.371      270299.086     1958136.251      270477.037
     1957911.642      270699.476
#Sta/Elev= 30
       0 2295.85    38.9  2276.8    48.6 2271.65    58.3 2265.79    68.1 2259.38
    77.8 2252.51    87.5 2245.16    97.2 2237.38   126.4 2212.99   136.1 2205.18
   145.8 2197.78   155.6 2190.99   165.3 2184.81     175 2179.31   184.7 2174.51
   194.5 2170.47   204.2 2167.66   213.9 2165.95   223.6 2165.91   243.1 2168.48
   262.5 2170.15   310.8 2171.59   368.3 2174.21   377.9 2175.15   387.5 2177.88
   397.1 2182.17     445 2205.74   531.2 2250.26   540.8 2255.28   607.8  2291.9
#Mann= 3 , 0 , 0
       0      .1       0   223.6    .045       0   243.1      .1       0
Bank Sta=223.6,243.1
XS Rating Curve= 0 ,0
Exp/Cntr=0.3,0.1

Type RM Length L Ch R = 1 ,6562    ,410.9,415.9,420.6
XS GIS Cut Line= 3
     1957974.576      270021.308     1957840.895      270105.075
     1957639.506      270271.742
#Sta/Elev= 30
       0  2253.3    18.6 2241.21    74.2 2204.75    83.5 2198.72   102.1 2186.88
   111.4 2180.76   120.6 2174.45   129.9 2168.24   139.2 2162.99   148.5 2160.36
   157.8 2159.59   167.4 2159.36   196.5 2158.99   206.2 2158.68   215.8    2158
   222.5 2157.26   225.5 2156.93   235.2 2156.54   240.5 2157.04   244.9 2157.45
   254.6 2158.81   264.3 2159.78   283.6  2161.1   293.3 2161.93     303 2163.68
   312.7  2167.6   322.4 2172.53   380.4 2204.26   399.8 2214.56   419.2 2224.69
#Mann= 3 , 0 , 0
       0      .1       0   222.5    .045       0   240.5      .1       0
Bank Sta=222.5,240.5
XS Rating Curve= 0 ,0
Exp/Cntr=0.3,0.1

Type RM Length L Ch R = 1 ,6146.1  ,447,440.6,434.4
XS GIS Cut Line= 3
      1957729.35      269726.169     1957619.991      269784.657
     1957306.173      269960.544
#Sta/Elev= 28
       0 2210.08    19.1  2198.5    38.2 2186.78    57.2 2174.98    66.8 2168.79
    85.9 2153.66    95.4 2148.92    97.5 2148.69   104.9 2147.87   115.5 2148.82
     124  2149.9   133.7 2151.02   182.4 2156.43   221.2  2160.9   308.8 2170.73
   318.5 2172.04   328.2 2174.09   337.9 2176.98   347.6 2180.38   357.4 2184.05
   376.8 2191.52   386.5 2195.08   396.3 2198.53   415.7 2205.83   435.2 2213.52
   444.9  2217.6   454.6 2221.78   483.8 2234.79
#Mann= 3 , 0 , 0
       0      .1       0    97.5    .045       0   115.5      .1       0
Bank Sta=97.5,115.5
XS Rating Curve= 0 ,0
Exp/Cntr=0.3,0.1

Type RM Length L Ch R = 1 ,5705.5  ,330.6,329.3,327.5
XS GIS Cut Line= 3
     1957475.444      269326.864     1957332.214      269474.433
     1957175.964      269626.343
#Sta/Elev= 30
       0 2223.95    19.6  2214.3    29.4 2209.63    39.2 2205.17      49 2200.35
    58.8 2194.96    78.3 2184.42   127.3 2158.94   146.9 2148.63   156.7  2144.3
   166.5 2142.69   176.3 2142.32   195.9 2142.12   215.1 2142.06   224.6 2141.87
   227.2 2141.67   234.1 2141.14   245.2 2139.97     253 2139.38   262.5    2142
     272  2145.4   281.4 2148.44   290.9  2150.9   300.4 2153.81   309.9 2157.41
   347.8 2172.71   395.2 2192.22   404.6 2196.27   414.1  2200.8   423.6  2205.9
#Mann= 3 , 0 , 0
       0      .1       0   227.2    .045       0   245.2      .1       0
Bank Sta=227.2,245.2
XS Rating Curve= 0 ,0
Exp/Cntr=0.3,0.1

Type RM Length L Ch R = 1 ,5376.2  ,507,505.5,504
XS GIS Cut Line= 3
     1957215.027      269138.062     1957086.989       269274.78
     1956961.121       269431.03
#Sta/Elev= 29
       0 2207.64     9.4 2202.28    28.1 2191.44    37.5 2185.82    46.8 2180.16
    84.3 2157.69    93.7 2151.79     103 2145.39   112.4 2138.63   121.8 2135.14
   131.1 2134.29   133.8 2134.56   151.8 2136.33   159.2 2136.92     216 2140.06
   244.6 2141.81   254.2 2142.48   263.8 2143.19   273.3 2144.14   282.9 2145.55
   292.4  2147.9     302 2150.68   321.1 2156.41   330.6 2159.53   340.2 2163.27
   349.7 2167.75   359.3 2172.68   368.8 2177.44     388 2186.85
#Mann= 3 , 0 , 0
       0      .1       0   133.8    .045       0   151.8      .1       0
Bank Sta=133.8,151.8
XS Rating Curve= 0 ,0
Exp/Cntr=0.3,0.1

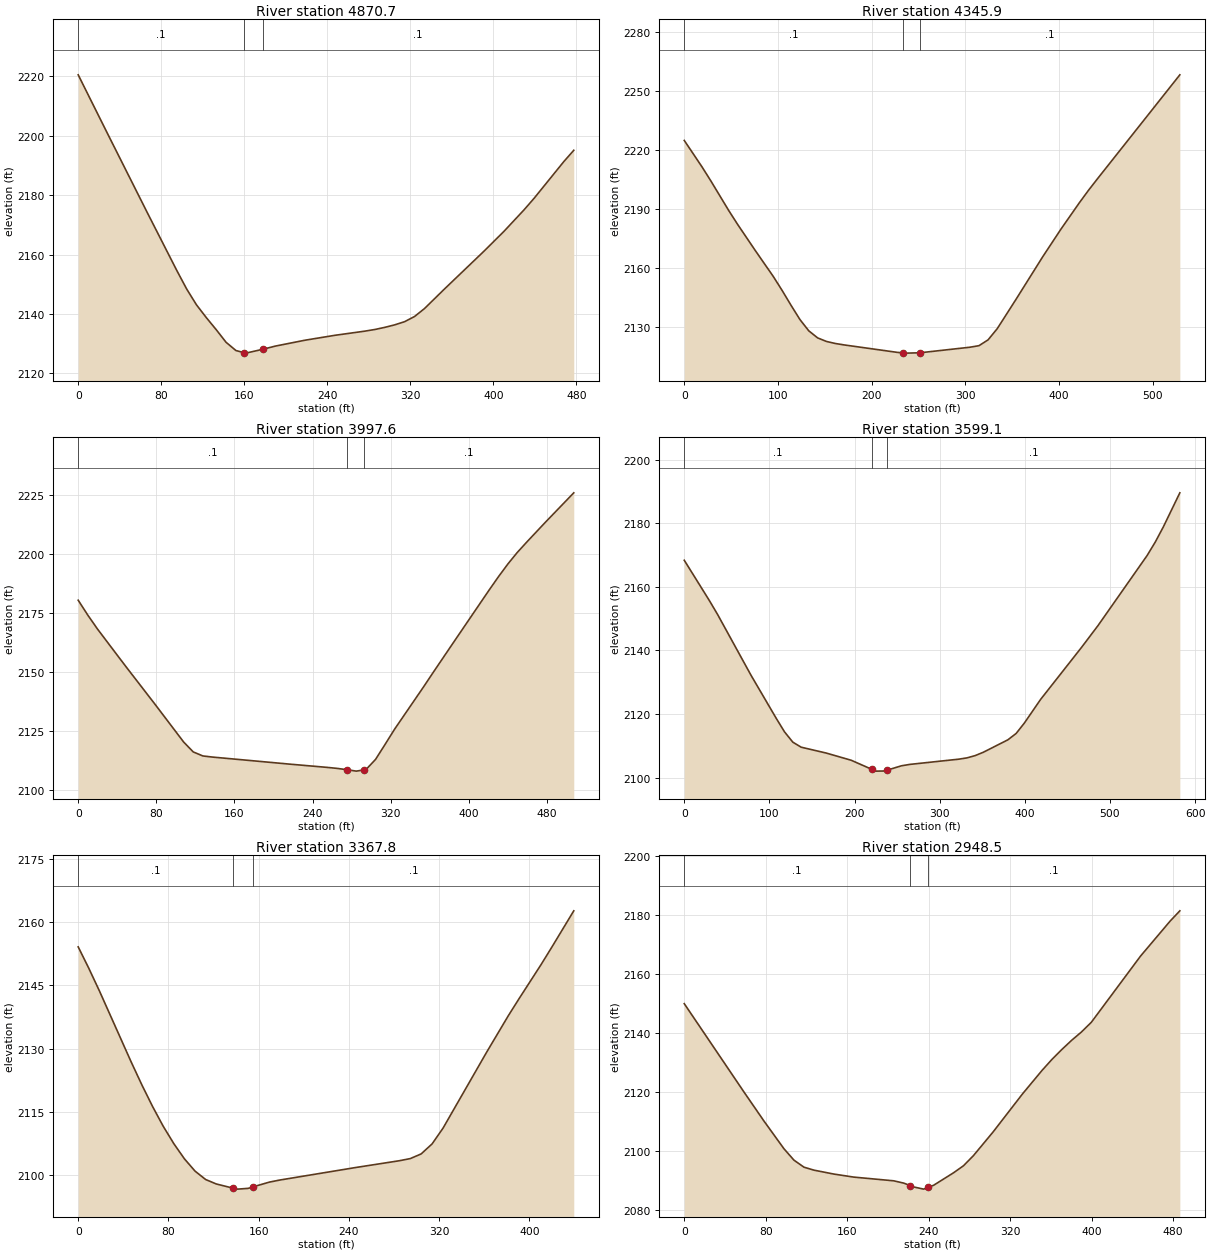
Type RM Length L Ch R = 1 ,4870.7  ,522.6,524.8,526.7
XS GIS Cut Line= 3
      1956800.53      268895.006     1956661.642      269051.256
     1956509.732       269272.61
#Sta/Elev= 30
       0 2220.52    28.5 2200.58    66.5 2174.19      95 2154.67   104.5 2148.44
     114 2143.09   123.5 2138.78     133 2134.74   142.5 2130.49     152 2127.72
   159.7 2127.01   161.5 2126.85   177.7 2128.13     190 2129.22   218.6  2131.2
   247.4 2132.85   276.2 2134.25   285.8  2134.8   295.4 2135.52   304.9 2136.36
   314.5 2137.43   324.1 2139.18   333.7 2141.86   352.9 2148.43   391.2 2161.23
   410.4  2167.9   429.6 2175.08   439.2 2178.93   467.9 2191.31   477.5 2195.12
#Mann= 3 , 0 , 0
       0      .1       0   159.7    .045       0   177.7      .1       0
Bank Sta=159.7,177.7
XS Rating Curve= 0 ,0
Exp/Cntr=0.3,0.1

Type RM Length L Ch R = 1 ,4345.9  ,340.7,348.3,355.8
XS GIS Cut Line= 3
     1956446.798      268532.593      1956265.51      268727.117
     1956097.405      268929.728
#Sta/Elev= 30
       0  2224.9      19 2211.39    28.5 2204.19    47.5 2189.16      57 2182.09
      76 2168.67      95 2155.61   104.5 2148.43     114 2140.88   123.5 2133.62
     133 2127.83   142.4 2124.25     152 2122.41   161.4 2121.38   170.9 2120.65
   227.9 2116.84   233.5 2116.63   237.4 2116.48   251.5 2116.65   304.9 2119.48
   314.7 2120.28   324.4 2123.23   334.2 2128.94   353.7 2143.48   382.9  2165.7
   402.4  2179.8   421.9 2193.13   431.7 2199.51   441.4 2205.46   529.2 2258.35
#Mann= 3 , 0 , 0
       0      .1       0   233.5    .045       0   251.5      .1       0
Bank Sta=233.5,251.5
XS Rating Curve= 0 ,0
Exp/Cntr=0.3,0.1

Type RM Length L Ch R = 1 ,3997.6  ,382.5,398.5,414.5
XS GIS Cut Line= 3
     1956277.527      268356.812     1955973.708      268517.402
     1955834.819      268604.207
#Sta/Elev= 30
       0 2180.33     9.8 2174.05    19.6 2168.22    39.3 2157.44    49.1  2152.1
    78.6  2136.3     108 2120.27   117.8 2116.09   127.6 2114.39   137.5 2113.91
     216 2110.94   255.3 2109.53   265.1 2109.12   275.1 2108.56   284.7 2107.96
   293.1  2108.5   294.6  2108.6   304.4  2112.9   314.2 2119.27     324 2125.75
   353.3 2143.45   362.9  2149.4   382.2  2161.2   420.7 2184.61   430.4 2190.34
     440  2195.7   449.6 2200.57   459.3 2204.96   478.5 2213.41   507.4  2225.8
#Mann= 3 , 0 , 0
       0      .1       0   275.1    .045       0   293.1      .1       0
Bank Sta=275.1,293.1
XS Rating Curve= 0 ,0
Exp/Cntr=0.3,0.1

Type RM Length L Ch R = 1 ,3599.1  ,234.4,231.3,228.1
XS GIS Cut Line= 3
     1956203.742      268168.009     1955943.326      268120.266
     1955626.485      268137.628
#Sta/Elev= 30
       0 2168.36    29.4 2155.72    39.2 2151.28    78.4 2132.18   107.9 2118.68
   117.7 2114.39   127.5 2111.13   137.3 2109.54   166.7  2107.7   196.1 2105.43
   220.6 2102.54   225.5 2102.01   235.3 2102.05   238.6 2102.34     255 2103.68
   264.8 2104.12   322.4 2105.77   332.1 2106.18   341.7  2106.9   351.3 2107.95
   380.1 2111.86   389.8 2113.86   399.4 2117.11   418.6 2124.59   466.7 2140.97
   485.9 2147.78   543.6 2169.83   553.2 2174.07   562.8 2178.91   582.1 2189.58
#Mann= 3 , 0 , 0
       0      .1       0   220.6    .045       0   238.6      .1       0
Bank Sta=220.6,238.6
XS Rating Curve= 0 ,0
Exp/Cntr=0.3,0.1

Type RM Length L Ch R = 1 ,3367.8  ,433.3,419.3,404.8
XS GIS Cut Line= 3
     1956205.912      267924.954      1956008.43      267914.103
     1955767.544      267931.464
#Sta/Elev= 30
       0  2154.1     9.4 2149.03    18.8 2143.68    47.1 2126.78    56.5  2121.4
    65.9 2116.34    75.3 2111.67    84.8 2107.51    94.2 2103.92   103.6 2101.02
     113 2099.03   122.4 2097.98   137.1    2097   141.3 2096.76   150.7 2096.94
   155.1 2097.31   169.5 2098.42   178.9 2098.92   246.1 2101.88   284.7 2103.48
   294.4 2103.99     304 2105.09   313.7 2107.46   323.4 2111.19     362 2129.14
   381.3 2137.81     391 2141.92   410.3  2149.9     420  2154.1   439.3 2162.63
#Mann= 3 , 0 , 0
       0      .1       0   137.1    .045       0   155.1      .1       0
Bank Sta=137.1,155.1
XS Rating Curve= 0 ,0
Exp/Cntr=0.3,0.1

Type RM Length L Ch R = 1 ,2948.5  ,552.1,549.9,548
XS GIS Cut Line= 3
     1956054.003      267449.693      1955817.91      267589.026
     1955617.805      267660.197
#Sta/Elev= 30
       0 2149.98    58.7 2119.96    78.3 2110.12    97.9 2100.73   107.7 2096.87
   117.5 2094.49   127.3 2093.48   146.9 2092.15   166.4 2091.12   205.6 2089.86
   215.4 2089.09   221.7 2088.25   225.2 2087.78     235 2087.04   239.7 2087.67
   244.8 2088.35   264.4  2092.6   274.1 2094.97   283.8 2098.38   303.1 2106.41
   332.1 2119.38   351.4  2127.4     361 2131.08   370.7 2134.44   380.3 2137.55
     390  2140.4   399.6 2143.66   447.9 2166.12   476.9 2177.98   486.5 2181.49
#Mann= 3 , 0 , 0
       0      .1       0   221.7    .045       0   239.7      .1       0
Bank Sta=221.7,239.7
XS Rating Curve= 0 ,0
Exp/Cntr=0.3,0.1

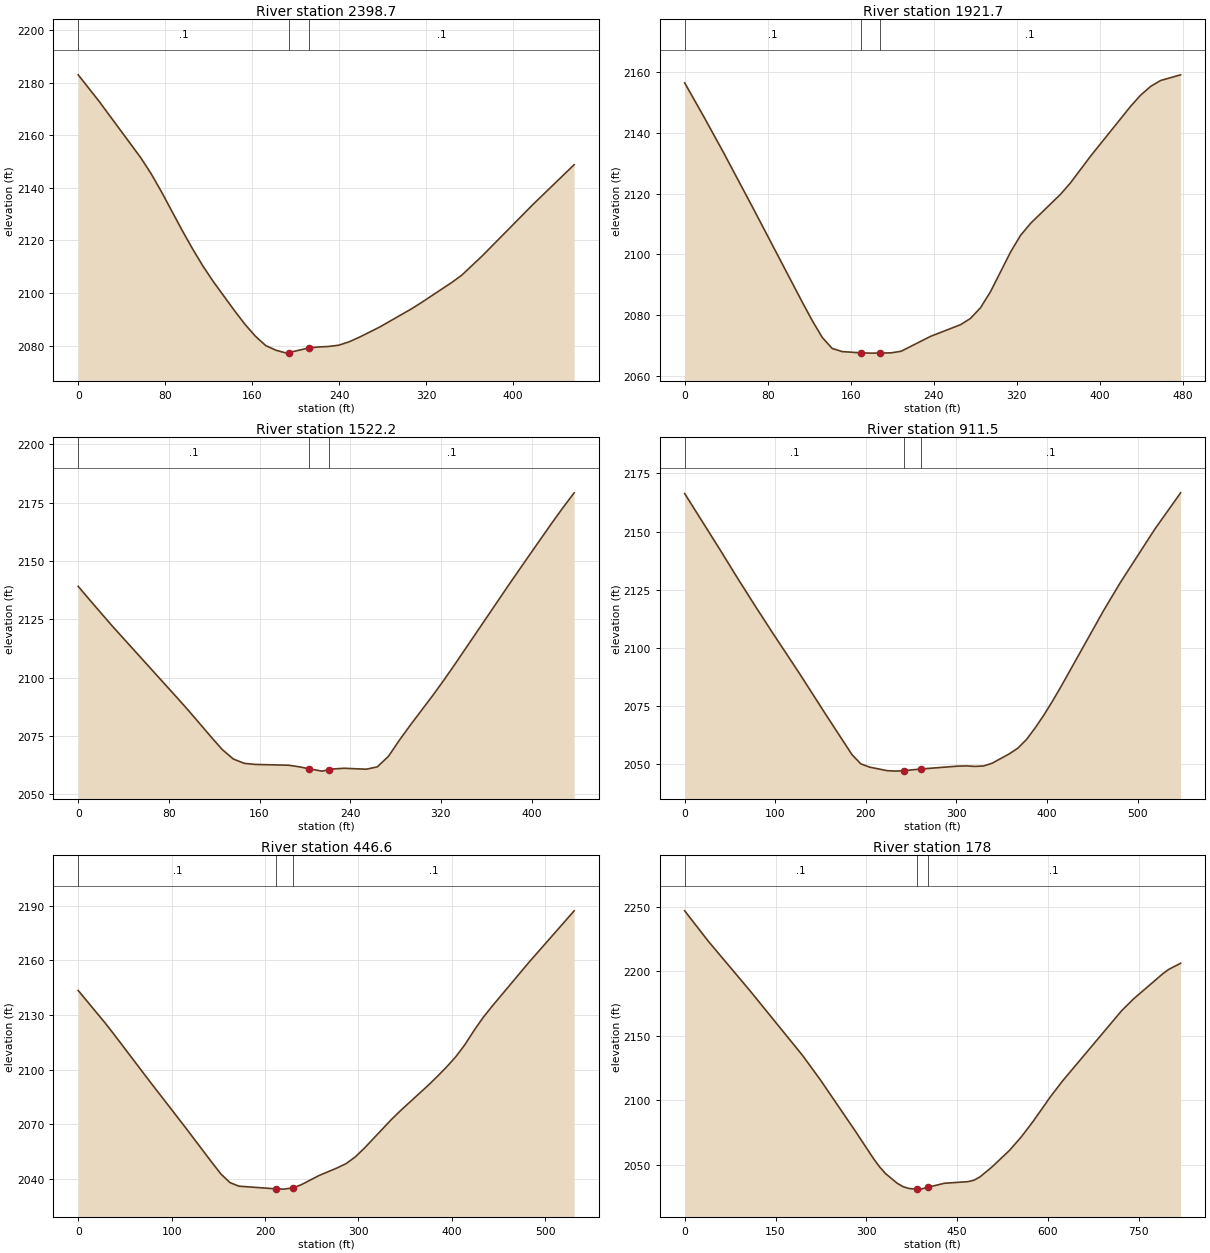
Type RM Length L Ch R = 1 ,2398.7  ,473.4,477,480.5
XS GIS Cut Line= 3
     1955761.034      266978.773      1955548.36      267126.343
      1955394.28      267250.041
#Sta/Elev= 30
       0 2182.99    19.2 2172.93    57.5 2151.49    67.1 2145.39    76.7 2138.45
    95.9 2123.64   105.5 2116.62     115  2110.1   124.6 2104.19   143.8  2093.3
   153.4 2088.13     163 2083.59   172.6 2079.99   182.2  2078.2   191.8 2077.13
     194 2077.36     212 2079.07   220.5 2079.46   230.1 2079.65   239.7 2080.14
   249.3 2081.43   258.9 2083.21   277.7 2087.11   305.9 2093.78   315.3 2096.21
   343.5 2103.93     353 2106.79   371.8 2114.11   418.8  2133.8   456.4  2148.8
#Mann= 3 , 0 , 0
       0      .1       0     194    .045       0     212      .1       0
Bank Sta=194,212
XS Rating Curve= 0 ,0
Exp/Cntr=0.3,0.1

Type RM Length L Ch R = 1 ,1921.7  ,392,399.5,407
XS GIS Cut Line= 3
     1955463.725      266651.082     1955242.371      266759.589
     1955021.017      266826.864
#Sta/Elev= 30
       0 2156.45      19 2144.97    37.9 2133.21    66.4 2114.89   113.8 2083.95
   123.3 2077.97   132.7 2072.59   142.2 2069.01   151.7 2067.99   170.1 2067.56
   180.2 2067.48   188.1  2067.5   199.1 2067.58   208.6  2068.1     237 2073.01
   265.8 2076.84   275.4  2078.9   285.1 2082.43   294.7  2087.7     314 2100.74
   323.6 2106.22   333.3 2110.19   362.2 2119.78   371.8 2123.53   391.1 2132.31
   429.7 2148.72   439.3 2152.38     449 2155.28   458.6 2157.22   477.9 2159.09
#Mann= 3 , 0 , 0
       0      .1       0   170.1    .045       0   188.1      .1       0
Bank Sta=170.1,188.1
XS Rating Curve= 0 ,0
Exp/Cntr=0.3,0.1

Type RM Length L Ch R = 1 ,1522.2  ,606,610.7,615.3
XS GIS Cut Line= 3
     1955371.277      266331.638     1955032.735      266381.117
     1954938.985      266399.346
#Sta/Elev= 30
       0 2139.13     9.8  2133.5    29.3 2122.51      88 2090.93    97.8 2085.57
   117.3 2074.49   127.1 2069.08   136.9 2065.02   146.6 2063.16   156.4  2062.7
   185.7 2062.37   195.5 2061.65   203.4 2060.85   215.1 2059.83   221.4 2060.43
   224.8 2060.75   234.6 2061.06   254.2 2060.65   263.9 2061.66   273.7 2066.16
   283.5 2073.18   293.3 2079.73   312.8 2092.27   322.6 2098.85   332.4  2105.7
   380.3 2140.02   399.4 2153.42   418.5 2166.68   428.1 2173.13   437.6 2179.26
#Mann= 3 , 0 , 0
       0      .1       0   203.4    .045       0   221.4      .1       0
Bank Sta=203.4,221.4
XS Rating Curve= 0 ,0
Exp/Cntr=0.3,0.1

Type RM Length L Ch R = 1 ,911.5   ,456.5,464.8,472.9
XS GIS Cut Line= 3
     1955472.839      265779.555     1955152.527      265766.534
     1954925.964       265776.95
#Sta/Elev= 30
       0 2166.34    38.9 2142.25    58.3 2129.98    77.7 2118.04    97.1 2106.36
   126.3 2089.16   155.4 2071.47   184.6 2054.03   194.3 2050.05     204 2048.61
   223.4 2047.09   233.2 2046.88   242.3 2047.09   260.3 2047.78   301.2 2049.02
   310.9 2049.12   320.6 2048.91     330  2049.1   339.5 2050.31   358.4 2054.33
   367.8 2056.78   377.3  2060.5   386.7  2065.4   396.2 2070.86   405.6 2076.76
   415.1 2083.07   462.3 2115.93   481.2 2128.25     519 2151.08   547.4 2166.66
#Mann= 3 , 0 , 0
       0      .1       0   242.3    .045       0   260.3      .1       0
Bank Sta=242.3,260.3
XS Rating Curve= 0 ,0
Exp/Cntr=0.3,0.1

Type RM Length L Ch R = 1 ,446.6   ,274.1,268.6,263
XS GIS Cut Line= 3
     1955550.964      265435.805     1955293.152      265334.242
     1955040.548        265308.2
#Sta/Elev= 30
       0 2143.45    28.7 2125.68    38.2 2119.43    76.4 2093.62   114.7 2068.23
   143.3 2048.84   152.9 2042.54   162.4  2037.9     172  2035.9   212.3 2034.39
   219.8 2034.27   230.3 2034.96   238.9 2036.71     258 2041.78   277.1  2045.9
   286.9 2048.31   296.6 2051.96   306.4 2056.79   335.7 2072.73   345.5 2077.61
   374.8 2091.36   384.5  2096.2   394.3 2101.34   404.1 2106.93   413.8 2113.51
   423.6 2121.29   433.4  2128.5   443.1 2134.74   482.2 2158.69     531 2187.23
#Mann= 3 , 0 , 0
       0      .1       0   212.3    .045       0   230.3      .1       0
Bank Sta=212.3,230.3
XS Rating Curve= 0 ,0
Exp/Cntr=0.3,0.1

Type RM Length L Ch R = 1 ,178     ,176.1,178,179.8
XS GIS Cut Line= 3
     1955837.156      265184.835      1955432.71      265120.512
     1955030.378      265043.861
#Sta/Elev= 30
       0 2246.85      39 2223.33   107.3 2185.29     195 2134.67   224.3  2115.8
   282.8 2075.58     312 2054.83   321.8  2048.6   331.5 2043.41     351 2035.83
   360.8 2033.18   370.5 2031.78   383.4  2031.3     390 2031.29   401.4 2032.68
     429 2035.84     468 2037.08   477.8  2038.2   487.5 2040.69     507 2048.23
   536.3 2061.22   555.8 2071.66   575.3 2083.66   604.6 2103.16   624.1 2115.07
   721.6 2169.45   741.1 2178.53   789.8 2198.16   799.6 2201.52   819.1 2206.24
#Mann= 3 , 0 , 0
       0      .1       0   383.4    .045       0   401.4      .1       0
Bank Sta=383.4,401.4
XS Rating Curve= 0 ,0
Exp/Cntr=0.3,0.1

Chan Stop Cuts=-1
Use User Specified Reach Order=0
Composite Channel Slope=5